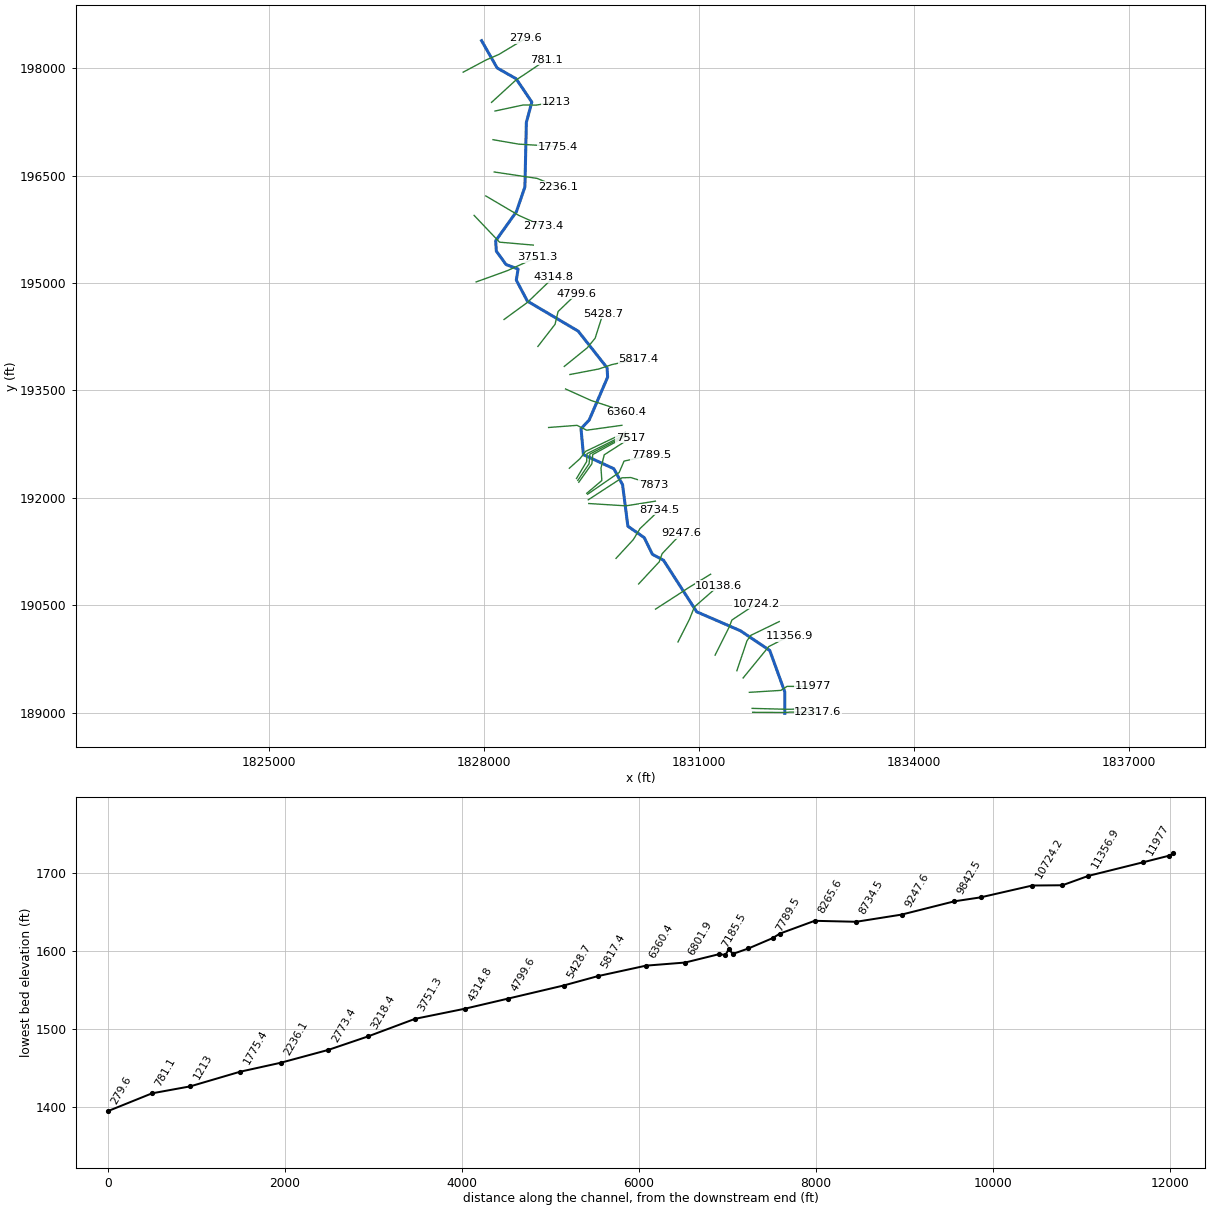
--- LtlWhtOkCr.prj (project) ---

Proj Title=LtlWhtOkCr
Current Plan=p01
Default Exp/Contr=0,0
English Units
Geom File=g01
Flow File=f01
Plan File=p01
BEGIN DESCRIPTION:
END DESCRIPTION:
DSS Export Rating Curves= 0
DSS Export Rating Curve Sorted= 0
DSS Export Volume Flow Curves= 0
DXF OffsetX= 0
DXF OffsetY= 0
DXF ScaleX= 0
DXF ScaleY= 0

--- LtlWhtOkCr.p01 (plan) ---

Plan Title=Floodplain
Program Version=4.00
Geom File=g01
Flow File=f01
K Sum by GR=0
Std Step Tol=0.01
Critical Tol=0.01
Num of Std Step Trials=20
Max Error Tol=0.3
Flow Tol Ratio=0.001
Split Flow NTrial=30
Split Flow Tol=0.02
Split Flow Ratio=0.02
Log Output Level=0
Friction Slope Method=1
Unsteady Friction Slope Method=2
Unsteady Bridges Friction Slope Method=1
Global Log Level=0
CheckData=False
Run HTab=0
Run UNet=0
Run PostProcess=0
UNET Theta=0
UNET Theta Warmup=0
UNET ZTol=0
UNET ZSATol=0
UNET MxIter=0
UNET MaxInSteps=0
UNET DtIC=0
UNET DtMin=0
UNET MaxCRTS=0
UNET WFStab=0
UNET SFStab=0
UNET WFX=0
UNET SFX=0
UNET DSS MLevel=0
UNET DZMax Abort=0
UNET Convert EG Bridges=0
UNET Use Existing IB Tables=0
UNET Froude Limit=0
UNET Froude Power=0
Write IC File=0
Echo Input=False
Echo Output=False
Write Detailed=0

--- LtlWhtOkCr.f01 (steady flow) ---

Flow Title=NFF Regression Equation
Program Version=4.00
Number of Profiles=1
Profile Names=P100yr
River Rch & RM=LtlWhtOkCr,Main      ,12317.6
515.7213
River Rch & RM=LtlWhtOkCr,Main      ,12271.1
515.8717
River Rch & RM=LtlWhtOkCr,Main      ,11977
597.6433
River Rch & RM=LtlWhtOkCr,Main      ,11356.9
608.8225
River Rch & RM=LtlWhtOkCr,Main      ,11063.3
696.8771
River Rch & RM=LtlWhtOkCr,Main      ,10138.6
709.4129
River Rch & RM=LtlWhtOkCr,Main      ,9842.5
1107.956
River Rch & RM=LtlWhtOkCr,Main      ,7517
1156.872
River Rch & RM=LtlWhtOkCr,Main      ,7185.5
1382.756
River Rch & RM=LtlWhtOkCr,Main      ,5428.7
1452.293
River Rch & RM=LtlWhtOkCr,Main      ,279.6
1545.738
Boundary for River Rch & Prof#=LtlWhtOkCr,Main      ,1
Up Type=0
Dn Type=3
Dn Slope=0.031275

--- LtlWhtOkCr.g01 (geometry) ---

Geom Title=USGS 10m DEM
Program Version=4.00

River Reach=LtlWhtOkCr      ,Main
Reach XY= 30
     1832200.495      188993.204     1832200.495      189292.086
     1831990.776      189871.013     1831581.494      190146.196
     1830970.708      190410.899     1830507.669      191130.586
     1830352.849       191212.87     1830238.926      191445.794
      1830010.37      191605.281     1829936.277      192184.208
     1829814.464      192407.741     1829390.002      192603.647
     1829356.095      192966.575     1829470.373      193087.132
     1829727.813      193686.151     1829720.278        193815.5
     1829317.165      194327.868     1828607.634      194747.307
      1828453.17       195039.91     1828478.287      195194.375
     1828310.008      195257.165     1828174.381       195444.28
     1828165.591      195588.697     1828454.426      195994.323
     1828573.338       196341.17     1828593.642      197241.479
      1828669.73       197524.64     1828450.659      197850.404
     1828185.684      198001.101     1827968.501      198382.041

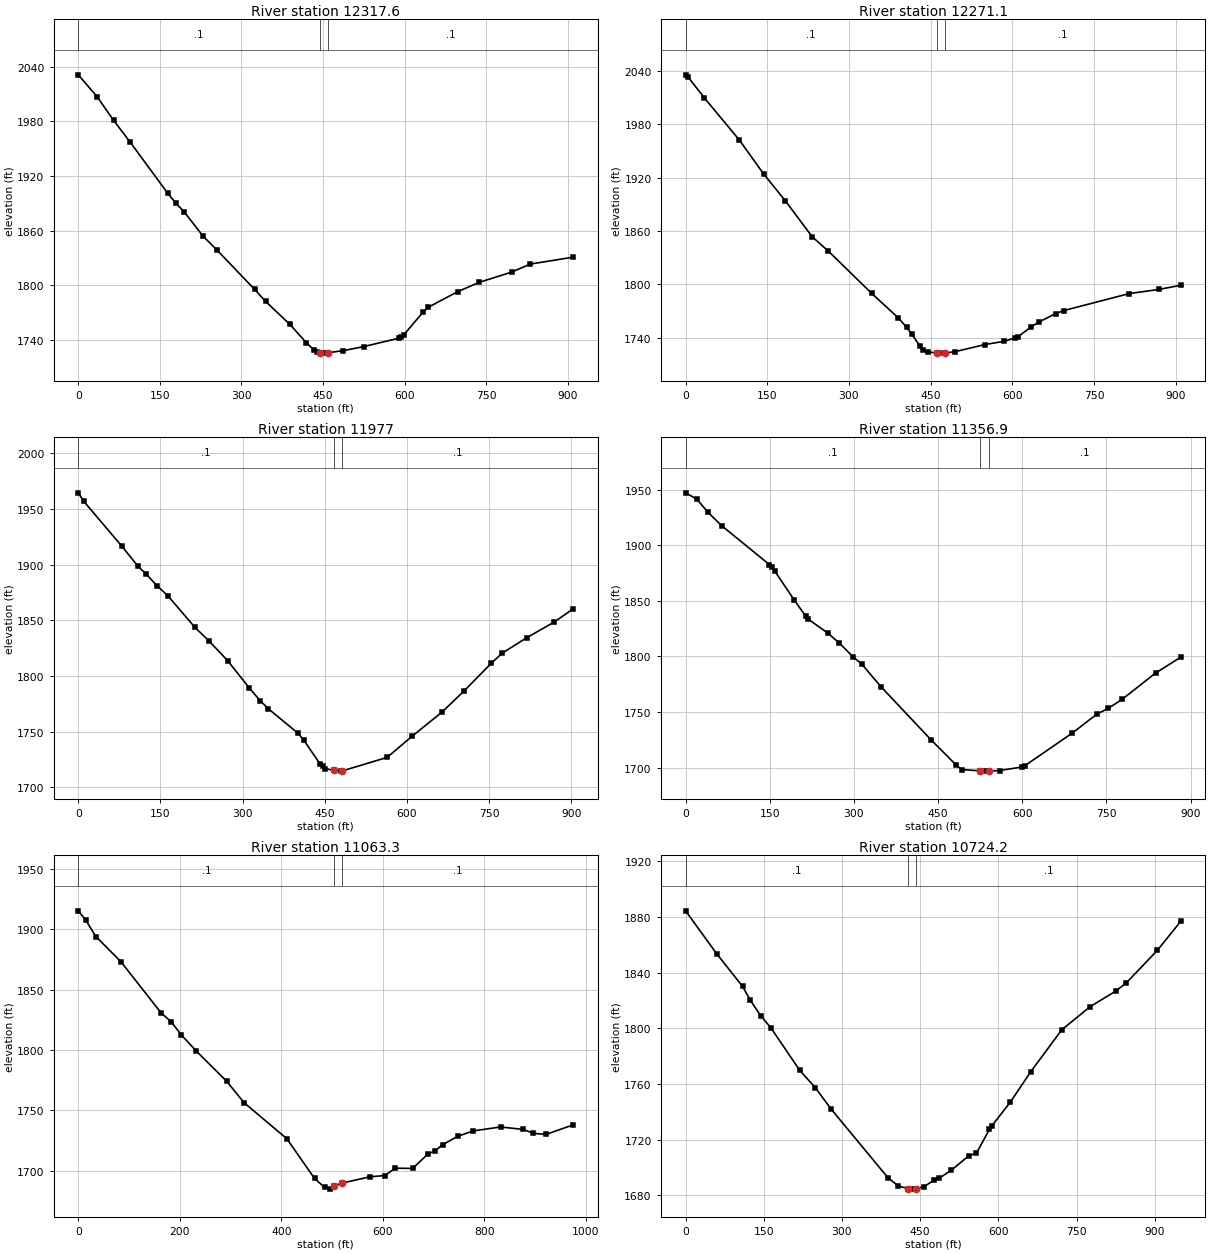
Type RM Length L Ch R = 1 ,12317.6 ,46.6,46.5,44.9
XS GIS Cut Line= 4
     1831751.835      189008.271     1832205.991      189005.571
     1832286.145      189011.621      1832662.17      189006.392
#Sta/Elev= 30
       0 2030.92    34.9 2006.67    64.9 1981.02    94.8 1957.58   164.7 1900.85
   179.7 1890.01   194.6 1880.71   229.6 1853.91   254.5  1839.1   324.4 1795.55
   344.4 1782.48   389.3 1757.13   419.2 1737.28   434.2 1728.82   439.2 1726.81
     444 1725.88   449.2  1725.7     459 1726.15   487.3  1728.4   525.1 1732.88
     589    1742   593.9 1743.23   598.9 1745.89   633.5 1770.27   643.4  1775.9
   697.8 1793.12   737.4 1803.33   796.8 1814.52   831.4 1823.37   910.6    1831
#Mann= 3 , 0 , 0
       0      .1       0     444    .045       0     459      .1       0
Bank Sta=444,459
XS Rating Curve= 0 ,0
Exp/Cntr=0.3,0.1

Type RM Length L Ch R = 1 ,12271.1 ,280.5,294.1,307.5
XS GIS Cut Line= 4
     1831744.727       189063.04     1832199.942      189050.942
     1832284.633      189050.942     1832653.644      189061.528
#Sta/Elev= 30
       0 2035.55       5 2032.75    34.6 2009.55      99 1962.11   143.5 1924.07
   183.1  1894.1   232.6 1853.55   262.3 1837.44   341.5 1790.16     391 1762.26
   405.9 1751.95   415.8 1743.88   430.6 1730.52   435.6 1726.89   445.5 1724.35
   461.6 1722.91   465.3 1722.86   476.6 1723.08   495.2 1724.52     550 1732.54
     585 1736.12   604.9  1739.9   609.9 1741.02   634.8 1752.47   649.8 1758.09
   679.8 1767.35   694.7  1770.7   814.4 1789.71   869.3 1794.42   909.2 1799.11
#Mann= 3 , 0 , 0
       0      .1       0   461.6    .045       0   476.6      .1       0
Bank Sta=461.6,476.6
XS Rating Curve= 0 ,0
Exp/Cntr=0.3,0.1

Type RM Length L Ch R = 1 ,11977   ,613,620.1,627.2
XS GIS Cut Line= 4
     1831705.406      189286.867     1832145.497      189314.089
     1832231.701      189370.045     1832591.638      189368.533
#Sta/Elev= 30
       0 1964.53     9.9 1956.94    79.3 1916.67     109 1898.46   123.9 1891.55
   143.7 1881.01   163.5 1871.98     213 1843.52   237.8 1831.79   272.5 1813.75
   312.1 1789.15   331.9 1777.72   346.8 1770.47   401.3  1748.3   411.2  1742.5
   440.9  1721.1   445.8 1718.76   450.7 1716.72   466.1 1715.12   480.1 1714.39
   481.1  1714.5   563.7 1726.73   608.7 1745.55   663.7 1767.37   703.7 1786.26
   753.7 1811.32   773.7 1820.43   818.7 1834.38   868.6  1848.4   903.6 1860.36
#Mann= 3 , 0 , 0
       0      .1       0   466.1    .045       0   481.1      .1       0
Bank Sta=466.1,481.1
XS Rating Curve= 0 ,0
Exp/Cntr=0.3,0.1

Type RM Length L Ch R = 1 ,11356.9 ,292.1,293.6,295
XS GIS Cut Line= 4
     1831619.203      189488.008     1831918.646      189853.994
     1831976.115      189925.074     1832258.923      190070.259
#Sta/Elev= 30
       0  1947.1    19.9  1941.5    39.8 1929.66    64.7  1917.4   149.3 1882.61
   154.3    1880   159.3 1876.47   194.1  1850.4     214 1836.28     219 1833.37
   253.9 1820.81   273.8 1812.14   298.7 1799.47   313.6 1793.31   348.4 1772.68
     438 1724.74   482.5 1702.18   492.1 1698.35   525.5 1697.09   535.4  1696.9
   540.5 1697.02   559.5 1697.45     599 1700.56     604 1701.57   688.5  1730.9
   733.2 1748.25     753 1753.26   777.9 1761.41   837.5  1785.1   882.2 1799.27
#Mann= 3 , 0 , 0
       0      .1       0   525.5    .045       0   540.5      .1       0
Bank Sta=525.5,540.5
XS Rating Curve= 0 ,0
Exp/Cntr=0.3,0.1

Type RM Length L Ch R = 1 ,11063.3 ,335.9,339.1,343.9
XS GIS Cut Line= 4
     1831531.487      189587.822     1831672.135      190005.228
     1831726.579      190082.358     1832122.812      190274.425
#Sta/Elev= 30
       0 1915.18    14.8 1907.43    34.6 1893.93    84.1    1873   163.3  1830.6
   183.1 1823.34   202.9 1812.52   232.6 1799.08     292 1774.25   326.6 1756.39
   410.8 1726.56   465.3 1693.72   485.2 1686.26   495.1 1684.88   504.5 1687.79
   519.5 1689.86   574.4 1695.09   604.1 1696.14   623.9  1702.2   658.6 1701.99
   688.2 1713.75   703.1  1716.8   717.9 1721.75   747.6 1728.57   777.3 1733.01
   831.7 1736.31   876.2  1734.3     896 1731.12   920.8 1730.09   975.2 1738.12
#Mann= 3 , 0 , 0
       0      .1       0   504.5    .045       0   519.5      .1       0
Bank Sta=504.5,519.5
XS Rating Curve= 0 ,0
Exp/Cntr=0.3,0.1

Type RM Length L Ch R = 1 ,10724.2 ,587,585.5,572
XS GIS Cut Line= 4
     1831227.515      189806.049     1831428.648      190206.369
      1831461.92      190295.598     1831800.379      190520.757
#Sta/Elev= 30
       0 1884.26    59.7 1853.45   109.5 1829.97   124.4 1819.96   144.4 1808.89
   164.3 1799.99     219 1769.77   248.9 1757.37   278.8 1742.19   388.3 1692.72
   408.2 1686.79   427.4 1684.88     438 1684.55   442.4 1684.96   457.5  1686.3
   476.6 1690.98   486.1 1692.28   509.9 1698.12   543.2 1708.45   558.1 1710.36
   582.9 1727.41   587.8 1730.07   622.6 1746.74   662.2  1768.8   721.7 1798.87
   776.2 1815.51   825.8 1826.79   845.6 1832.58   905.1 1855.92   949.8 1876.64
#Mann= 3 , 0 , 0
       0      .1       0   427.4    .045       0   442.4      .1       0
Bank Sta=427.4,442.4
XS Rating Curve= 0 ,0
Exp/Cntr=0.3,0.1

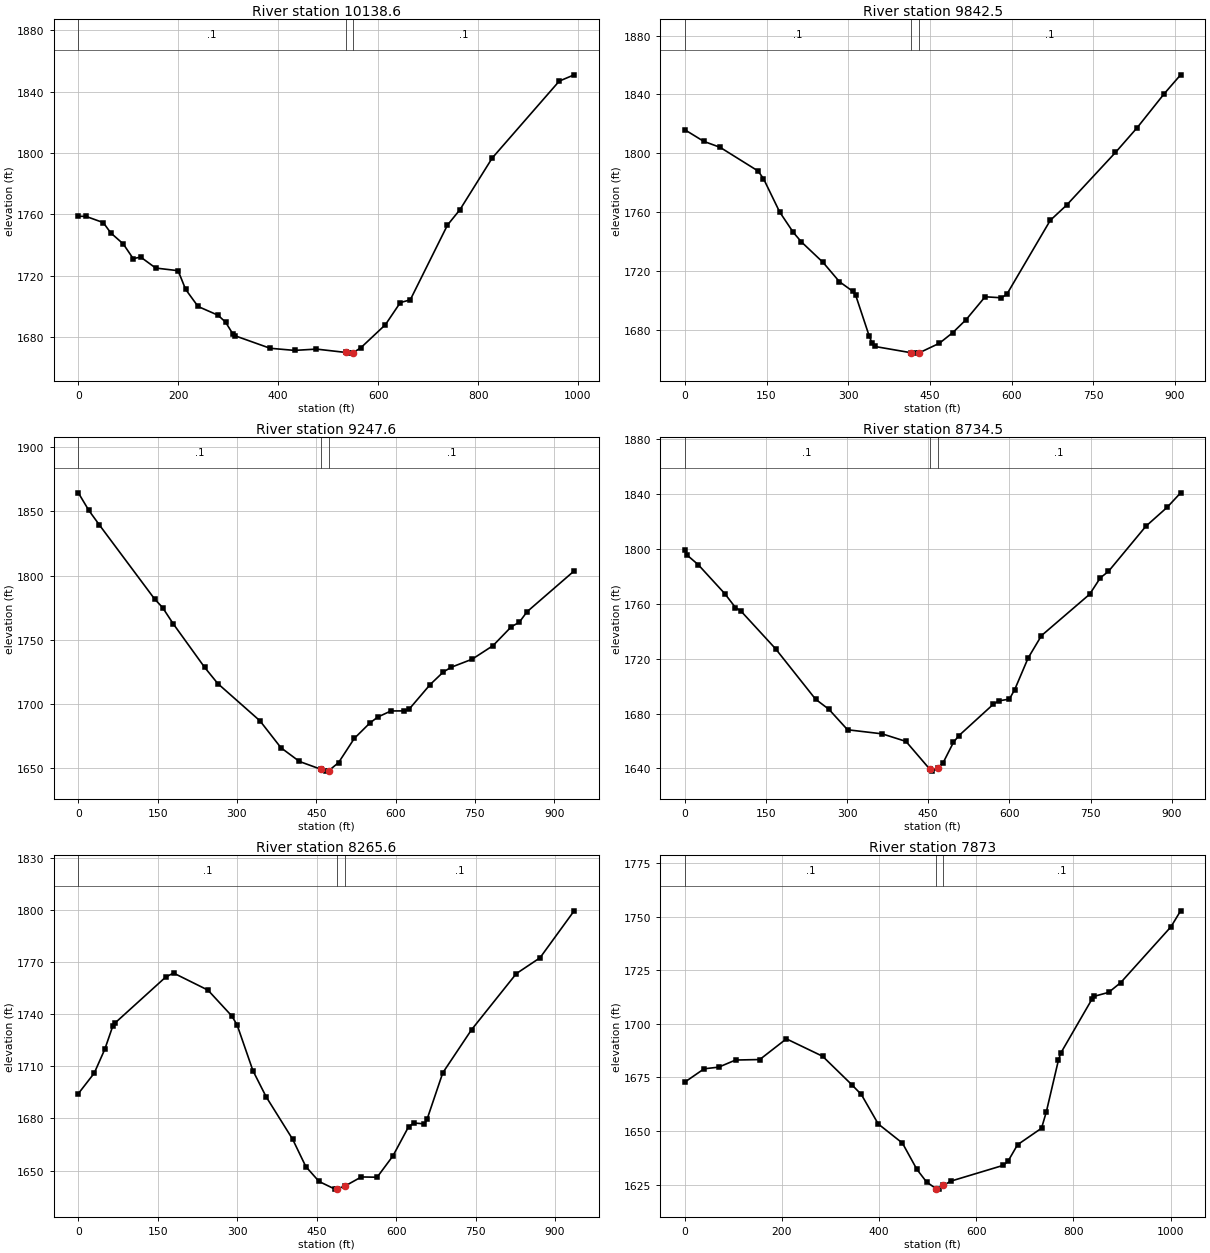
Type RM Length L Ch R = 1 ,10138.6 ,309.3,296.1,294
XS GIS Cut Line= 4
     1830709.699      189990.051     1830872.107      190310.721
      1830938.65      190478.591     1831278.926      190776.522
#Sta/Elev= 30
       0 1758.66      15 1758.63    49.9 1754.55    64.9 1747.82    89.9 1740.62
   109.8 1731.02   124.8 1732.04   154.8 1724.88   199.7 1723.15   214.7 1710.97
   239.6 1699.79   279.6 1694.08   294.6 1689.58   309.5 1681.74   314.5 1680.56
   383.8 1672.51   432.7 1671.12   476.6 1671.97   534.8  1669.8     545 1669.34
   549.8 1669.62   564.9  1672.7   614.6 1687.92   644.4 1702.35   664.3  1704.1
   738.8 1752.95   763.7 1762.96   828.3 1796.69   962.5 1846.91   992.3    1851
#Mann= 3 , 0 , 0
       0      .1       0   534.8    .045       0   549.8      .1       0
Bank Sta=534.8,549.8
XS Rating Curve= 0 ,0
Exp/Cntr=0.3,0.1

Type RM Length L Ch R = 1 ,9842.5  ,580.6,594.9,609
XS GIS Cut Line= 4
     1830396.459      190448.352     1830726.922      190661.584
     1830846.397      190740.226     1831165.171      190935.594
#Sta/Elev= 30
       0    1816    34.8  1808.1    64.7 1804.08   134.4    1788   144.4 1782.82
   174.2  1760.1   199.1 1746.32   214.1 1739.79   253.9 1725.85   283.8 1712.81
   308.6  1706.2   313.6 1703.68   338.5 1675.92   343.5 1671.26   348.5 1668.82
   415.1 1664.55   422.9 1664.27   430.1 1664.44   467.3 1670.97   491.9 1678.19
   516.6 1687.09   551.3 1702.54   581.2 1701.86   591.2 1704.25   670.9 1754.46
   700.8 1764.76   790.6 1800.57   830.4 1817.39   880.3 1840.56   910.2  1853.3
#Mann= 3 , 0 , 0
       0      .1       0   415.1    .045       0   430.1      .1       0
Bank Sta=415.1,430.1
XS Rating Curve= 0 ,0
Exp/Cntr=0.3,0.1

Type RM Length L Ch R = 1 ,9247.6  ,518,513.1,508.1
XS GIS Cut Line= 4
     1830160.487       190799.39     1830448.652      191109.237
     1830487.973       191221.15     1830760.392      191508.677
#Sta/Elev= 30
       0 1864.57    19.9 1850.83    39.8 1839.49   144.4 1781.58   159.3 1775.02
   179.2 1762.47     239 1728.22   263.8 1715.61   343.5 1686.55   383.3 1665.49
   418.2  1654.8   458.2  1648.8   467.6 1647.26   473.2 1647.42   492.3 1653.98
     522 1672.82   551.7 1684.94   566.5 1689.52   591.3 1694.25     616 1694.29
   625.9 1695.74   665.5 1714.89   690.3 1724.66   705.1 1728.34   744.8 1734.65
   784.4 1745.27     819 1760.02   833.9 1763.44   848.7 1771.72   937.8 1803.58
#Mann= 3 , 0 , 0
       0      .1       0   458.2    .045       0   473.2      .1       0
Bank Sta=458.2,473.2
XS Rating Curve= 0 ,0
Exp/Cntr=0.3,0.1

Type RM Length L Ch R = 1 ,8734.5  ,494.2,468.9,443.6
XS GIS Cut Line= 4
     1829845.068      191156.615      1830085.69      191417.754
     1830179.455      191572.013     1830455.381       191834.61
#Sta/Elev= 30
       0 1799.01     4.9 1795.26    24.7 1788.57      74 1767.36    93.7 1757.25
   103.6 1754.79   167.7 1727.27   241.7 1690.48   266.3 1683.14   300.8 1668.21
   364.8 1665.23   408.8 1659.72   452.5 1639.63   457.6 1638.06   467.5 1640.35
   477.1 1643.86   496.6 1659.05   506.3  1663.8   570.2 1686.78   580.1 1689.26
   599.9 1690.53   609.8 1697.46   634.6 1720.48   659.3 1736.83   748.3 1766.96
   768.1 1778.94     783 1783.58   852.2  1816.5   891.8 1830.41   916.5 1840.89
#Mann= 3 , 0 , 0
       0      .1       0   452.5    .045       0   467.5      .1       0
Bank Sta=452.5,467.5
XS Rating Curve= 0 ,0
Exp/Cntr=0.3,0.1

Type RM Length L Ch R = 1 ,8265.6  ,378,392.6,407.2
XS GIS Cut Line= 3
     1829464.296      191922.048     1829982.851      191889.604
     1830394.394        191954.9
#Sta/Elev= 30
       0 1694.32      30 1706.12      50  1719.9      65 1733.21    69.9 1735.18
   164.9 1761.45   179.8 1763.79   244.8 1753.95   289.8 1739.06   299.8 1733.92
   329.7 1707.55   354.7 1692.47   404.7 1668.04   429.6 1652.28   454.6  1643.7
   484.6  1639.3   488.3 1639.48   503.3 1641.03   534.4 1646.32   564.2 1646.16
     594 1658.39   623.7 1675.28   633.7  1677.4   653.5  1676.9   658.5 1679.52
   688.2 1706.31   742.8 1731.26   827.1 1763.47   871.8 1772.57   936.3 1799.64
#Mann= 3 , 0 , 0
       0      .1       0   488.3    .045       0   503.3      .1       0
Bank Sta=488.3,503.3
XS Rating Curve= 0 ,0
Exp/Cntr=0.3,0.1

Type RM Length L Ch R = 1 ,7873    ,82.9,83.5,84.1
XS GIS Cut Line= 4
     1829457.452      191973.734     1829928.632      192280.944
     1830051.139      192284.713     1830371.542      192184.823
#Sta/Elev= 30
       0 1672.83    39.8 1679.05    69.7 1679.81   104.5 1683.13   154.3 1683.36
   209.1 1693.01   283.7 1684.89   343.5 1671.69   363.4 1667.07   398.2 1653.33
     448  1644.4   477.9 1632.11   497.8 1626.25   517.1 1623.19   522.7 1622.94
   532.1 1624.65   547.6 1626.66   655.6 1634.03   665.4 1635.96     685 1643.64
   734.4 1651.35   744.3 1659.03     769 1682.93   773.9 1686.34     838 1711.44
     843 1712.86   872.6 1714.68   897.3 1719.22  1000.9 1745.28  1020.7  1752.7
#Mann= 3 , 0 , 0
       0      .1       0   517.1    .045       0   532.1      .1       0
Bank Sta=517.1,532.1
XS Rating Curve= 0 ,0
Exp/Cntr=0.3,0.1

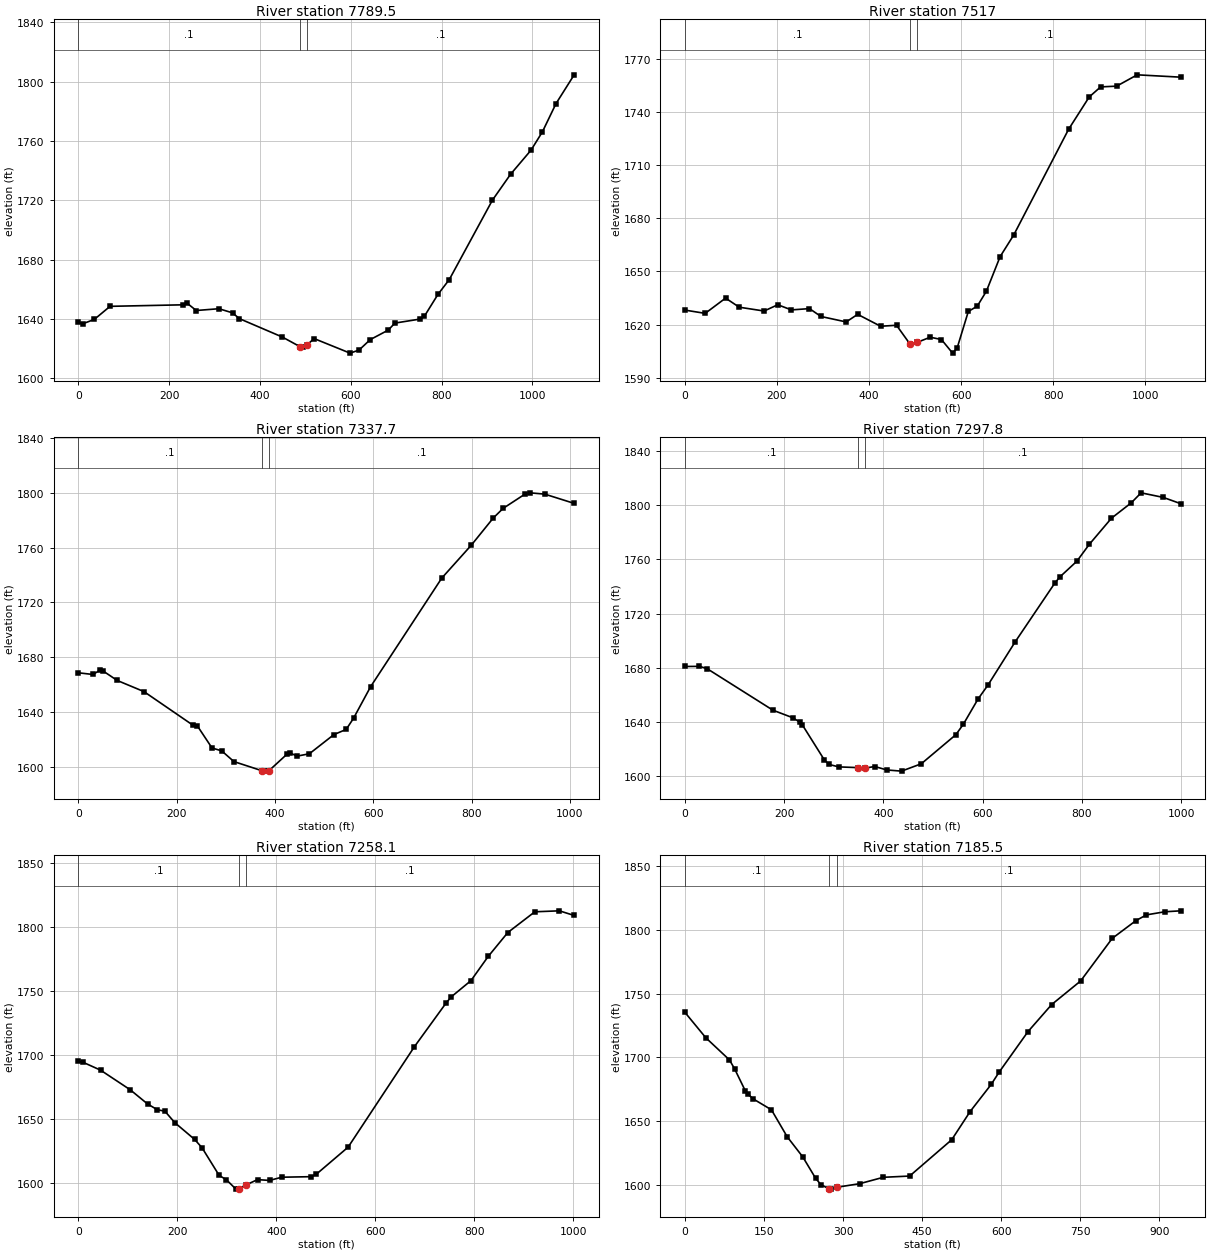
Type RM Length L Ch R = 1 ,7789.5  ,255,272.5,289.9
XS GIS Cut Line= 4
     1829449.121      192052.115     1829889.086      192355.405
     1829957.141      192514.201     1830333.183      192596.553
#Sta/Elev= 30
       0  1637.7      10 1636.88      35 1639.74    69.9 1648.59   229.7 1649.61
   239.7 1650.67   259.7 1645.78   309.6 1646.98   339.6 1644.21   354.6 1640.32
   449.5 1627.88   488.4 1621.39   494.4 1620.87   503.4 1622.56   519.4 1626.86
   598.5 1617.06   618.3 1619.12     643 1626.17   682.5 1632.56   697.3  1637.3
   752.1 1639.98   762.1 1641.86   792.1 1656.64   817.1 1666.64   912.1 1720.16
   952.1  1737.6   997.1 1753.82  1022.1 1766.14  1052.1 1785.18  1092.1 1804.58
#Mann= 3 , 0 , 0
       0      .1       0   488.4    .045       0   503.4      .1       0
Bank Sta=488.4,503.4
XS Rating Curve= 0 ,0
Exp/Cntr=0.3,0.1

Type RM Length L Ch R = 1 ,7517    ,147.4,179.3,183.2
XS GIS Cut Line= 5
     1829436.896      192065.036     1829647.112      192243.492
     1829635.013      192417.411     1829680.383      192601.916
     1830047.882      192837.841
#Sta/Elev= 30
       0 1628.17    44.3 1626.31    88.6 1634.93   118.2 1629.79   172.3 1627.63
   201.9 1631.18   231.4 1628.27   270.8 1628.99   295.7 1624.55   350.5 1621.47
   375.4 1625.76   425.2 1619.04   459.8 1619.59   489.5 1608.82   504.5 1609.92
   532.9 1612.84   557.3 1611.55   581.6 1603.86   591.4 1606.69   615.7 1627.37
   635.2 1630.39     655 1638.84   684.8 1658.36   714.5 1670.63   833.6 1730.29
   878.3 1748.51   903.1 1754.19   937.8  1754.6   982.5    1761  1076.8 1759.68
#Mann= 3 , 0 , 0
       0      .1       0   489.5    .045       0   504.5      .1       0
Bank Sta=489.5,504.5
XS Rating Curve= 0 ,0
Exp/Cntr=0.3,0.1

Type RM Length L Ch R = 1 ,7337.7  ,70.4,39.9,39.9
XS GIS Cut Line= 4
     1829325.521      192218.748     1829508.339      192476.955
     1829519.648      192605.116     1830013.445      192876.516
#Sta/Elev= 30
       0 1668.58    29.7 1667.34    44.5 1670.59    49.4 1670.12    79.1 1662.97
   133.5 1654.83   232.3 1630.49   242.2 1629.71   271.9 1613.64   291.7 1611.51
   316.4  1603.7   373.1 1597.06   380.7 1596.72   388.1 1597.15   425.2 1609.38
   430.2  1610.1     445 1607.68     470 1609.42   519.8 1623.41   544.8  1627.2
   559.7 1635.31   594.6 1658.48   739.2 1737.76   799.1 1761.74     844 1781.69
   863.9 1788.69   908.8 1799.22   918.7 1800.08   948.7 1799.13  1008.5 1792.37
#Mann= 3 , 0 , 0
       0      .1       0   373.1    .045       0   388.1      .1       0
Bank Sta=373.1,388.1
XS Rating Curve= 0 ,0
Exp/Cntr=0.3,0.1

Type RM Length L Ch R = 1 ,7297.8  ,38.8,39.7,41
XS GIS Cut Line= 4
     1829311.858      192244.523     1829469.157      192477.504
     1829481.029      192612.543     1829997.443      192881.138
#Sta/Elev= 30
       0 1680.93    29.6 1681.03    44.4 1679.45   177.5 1648.68     217 1643.18
   231.8 1639.86   236.7  1637.9   281.1 1611.99   290.8 1608.63   310.2 1606.83
   348.9  1606.3   363.9 1606.02   382.8 1607.11     407 1604.56   436.6 1603.71
   476.4 1609.13     546 1630.59     561 1638.24   590.8 1656.99   610.7 1667.22
   665.4 1699.06     745 1742.27     755 1746.84   789.8 1758.64   814.7 1771.01
   859.5 1790.38   899.3  1801.7   919.2  1809.1   963.9 1805.71   998.8 1801.12
#Mann= 3 , 0 , 0
       0      .1       0   348.9    .045       0   363.9      .1       0
Bank Sta=348.9,363.9
XS Rating Curve= 0 ,0
Exp/Cntr=0.3,0.1

Type RM Length L Ch R = 1 ,7258.1  ,82.3,72.5,68.8
XS GIS Cut Line= 4
     1829293.481       192271.52     1829434.835      192507.111
     1829440.489      192618.309     1829990.828      192893.479
#Sta/Elev= 30
       0 1695.25      10 1694.52      45 1688.44   104.9 1673.09   139.9 1662.02
   159.8 1657.48   174.8 1656.41   194.8 1647.45   234.8 1634.36   249.8 1627.86
   284.4 1606.23     299 1602.84   318.3  1595.5   324.2 1595.74   339.2 1598.87
   361.9 1602.93   386.1  1602.3   410.9 1604.81   470.4 1605.23   480.4 1607.05
   544.9 1628.31   678.8  1706.8   743.4 1741.26   753.3 1745.76     793 1758.42
   827.7 1777.26   867.4 1795.99     922 1812.19   971.6 1812.94  1001.4 1809.32
#Mann= 3 , 0 , 0
       0      .1       0   324.2    .045       0   339.2      .1       0
Bank Sta=324.2,339.2
XS Rating Curve= 0 ,0
Exp/Cntr=0.3,0.1

Type RM Length L Ch R = 1 ,7185.5  ,418.9,383.7,342
XS GIS Cut Line= 4
     1829193.409      192414.386     1829341.619      192547.472
     1829418.748      192648.799     1829972.265      192913.458
#Sta/Elev= 30
       0  1735.5    39.8 1715.45    84.7 1698.02    94.6 1690.88   114.5 1673.93
   119.5 1671.28   129.5 1667.45   164.3 1658.84   194.2 1637.63   223.7 1621.85
   248.2 1604.94     258 1600.13   272.9 1596.85   277.6 1596.54   287.9 1597.99
   331.5 1600.81   376.4 1605.83   426.3 1606.81   506.1 1635.34     541 1657.48
   580.9 1678.76   595.9 1688.38   650.8 1720.31   695.6  1741.5   750.5 1760.04
   810.4 1793.48   855.3 1807.41   875.2 1811.94   910.1 1814.37   940.1 1815.12
#Mann= 3 , 0 , 0
       0      .1       0   272.9    .045       0   287.9      .1       0
Bank Sta=272.9,287.9
XS Rating Curve= 0 ,0
Exp/Cntr=0.3,0.1

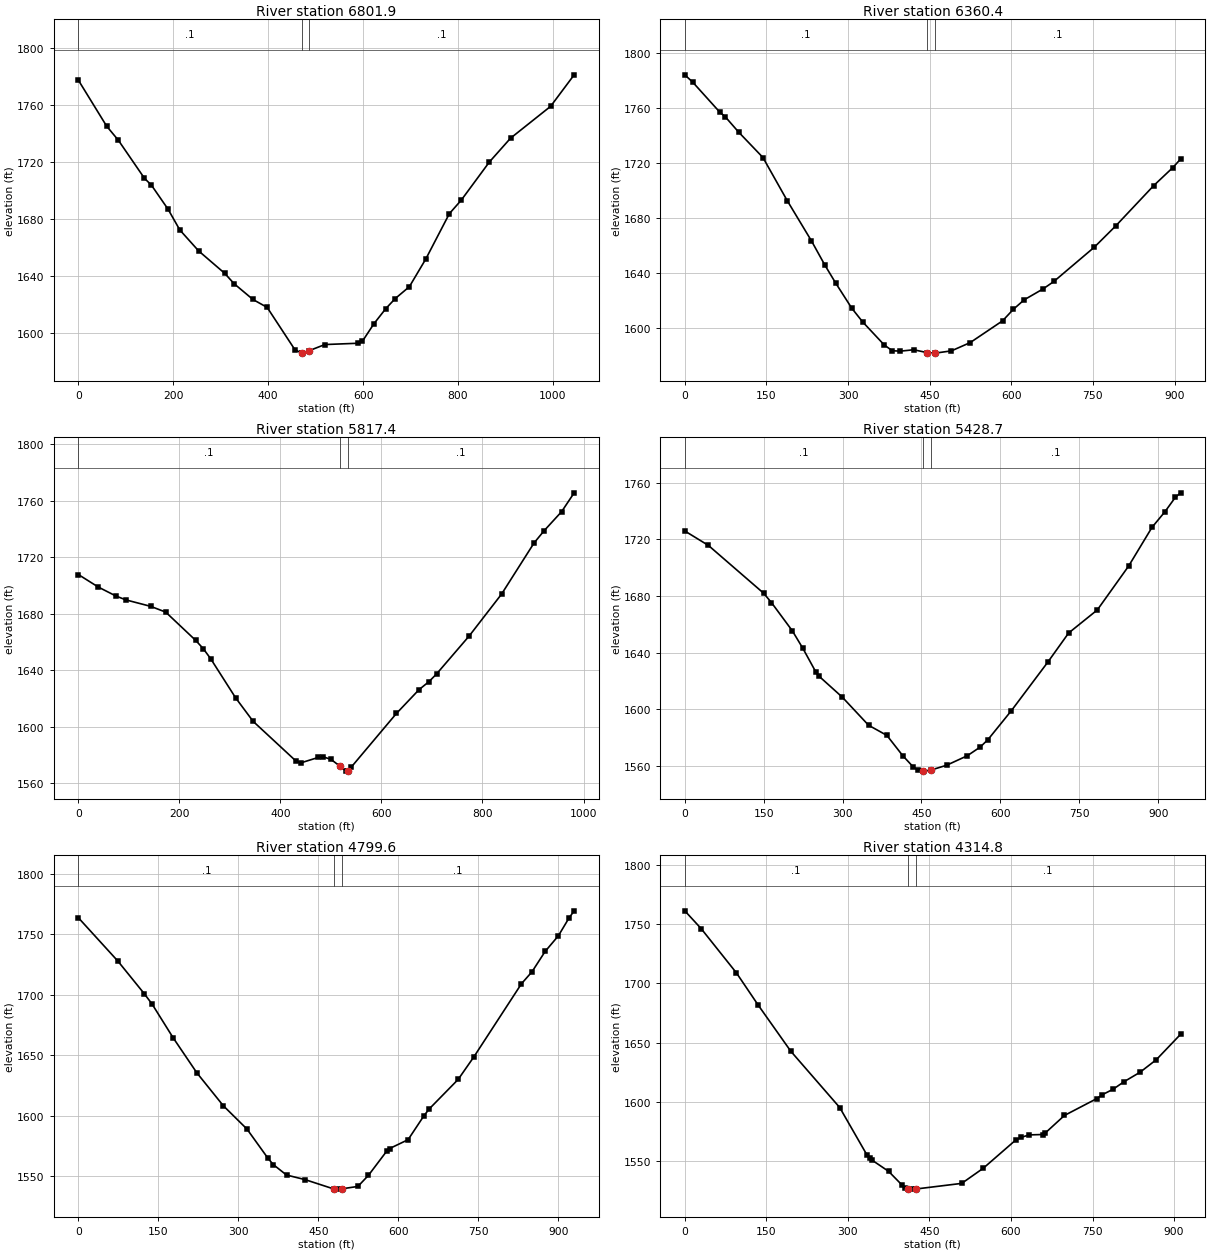
Type RM Length L Ch R = 1 ,6801.9  ,437.5,441.4,444.8
XS GIS Cut Line= 4
     1828904.162      192983.113     1829300.786      193013.273
     1829435.384      192945.218     1829926.589      193013.708
#Sta/Elev= 30
       0 1777.66    59.7 1745.29    84.5 1735.32   139.2 1708.72   154.1  1703.8
   188.9 1687.01   213.8 1672.37   253.6 1657.59   308.3 1641.91   328.2 1634.59
   367.9  1623.5   397.8 1617.95   456.2 1588.24   470.8 1585.81   471.1 1585.81
   486.1 1587.51   519.4 1591.84   588.3 1592.74   598.2 1594.02     623 1606.57
   647.8  1617.1   667.6 1624.14   697.4 1632.49   732.1 1651.99   781.7 1683.83
   806.5 1693.21     866 1720.13   910.6 1736.86     995 1759.24  1044.6 1781.38
#Mann= 3 , 0 , 0
       0      .1       0   471.1    .045       0   486.1      .1       0
Bank Sta=471.1,486.1
XS Rating Curve= 0 ,0
Exp/Cntr=0.3,0.1

Type RM Length L Ch R = 1 ,6360.4  ,529.5,543,557.1
XS GIS Cut Line= 4
     1829140.813      193520.723     1829501.927      193358.086
     1829628.963      193317.253     1829991.196      193196.765
#Sta/Elev= 30
       0 1784.13    14.8 1778.69    64.4 1756.95    74.3 1753.67      99 1742.46
   143.6 1724.03   188.1 1692.77   232.7 1663.47   257.4 1645.82   277.2 1632.82
   306.9 1614.46   326.7  1604.6   366.3 1587.86   381.2 1583.57     396 1583.26
   420.8 1584.28   445.3 1582.19   460.3 1581.83     490 1583.48   524.5 1589.49
     584 1605.32   603.8 1613.68   623.7 1620.58   658.4  1628.5   678.2  1633.9
   752.6 1658.84   792.2 1674.41   861.6 1703.55   896.4 1716.54   911.2 1722.91
#Mann= 3 , 0 , 0
       0      .1       0   445.3    .045       0   460.3      .1       0
Bank Sta=445.3,460.3
XS Rating Curve= 0 ,0
Exp/Cntr=0.3,0.1

Type RM Length L Ch R = 1 ,5817.4  ,376.1,388.8,401.4
XS GIS Cut Line= 4
      1829201.83      193722.501     1829604.766       193799.69
     1829784.734      193860.183     1830157.025      193942.793
#Sta/Elev= 30
       0 1707.81    39.5 1698.92    74.1 1692.63    93.9 1689.84   143.3 1685.23
     173 1681.15   232.3 1661.11   247.2  1655.3     262  1648.1   311.4 1620.36
     346 1603.72   430.2 1575.77   440.2 1574.25   475.2 1578.15   485.2 1578.49
   500.2 1576.74     518 1571.88   530.2 1568.42     533 1568.85   540.2 1571.24
   629.8 1609.36   674.4 1626.17   694.2  1631.9   709.1 1637.31   773.5 1664.15
   837.8 1693.92   902.2 1730.22     922 1738.84   956.7 1752.39   981.5 1765.72
#Mann= 3 , 0 , 0
       0      .1       0     518    .045       0     533      .1       0
Bank Sta=518,533
XS Rating Curve= 0 ,0
Exp/Cntr=0.3,0.1

Type RM Length L Ch R = 1 ,5428.7  ,617.7,629,639.9
XS GIS Cut Line= 4
     1829122.611      193835.262     1829444.458      194096.109
     1829553.346      194229.195     1829661.833      194568.775
#Sta/Elev= 30
       0 1725.99    44.9 1715.78   149.7 1682.08   164.7 1675.44   204.6 1655.38
   224.6    1643   249.6 1626.06   254.6 1623.59   299.5 1608.58   349.4 1588.76
   384.3 1581.56   414.3  1567.3   433.9 1559.47   443.8 1556.94   452.7 1556.38
   453.6 1556.34   467.7 1557.06   497.8  1560.5   537.1  1567.2   561.7 1573.36
   576.4 1578.61   620.9 1599.04   690.2 1633.35   729.8 1653.92   784.3 1670.21
   843.7 1701.12   888.3 1728.56     913 1739.65   932.8 1749.82   942.7 1752.94
#Mann= 3 , 0 , 0
       0      .1       0   452.7    .045       0   467.7      .1       0
Bank Sta=452.7,467.7
XS Rating Curve= 0 ,0
Exp/Cntr=0.3,0.1

Type RM Length L Ch R = 1 ,4799.6  ,502.9,484.8,471.2
XS GIS Cut Line= 4
     1828754.425      194114.289      1828993.78      194422.774
     1829036.126       194601.23     1829292.523      194848.149
#Sta/Elev= 30
       0 1763.83    74.1    1728   123.6 1701.05   138.4 1692.39   177.9 1664.52
   222.4 1635.54   271.8 1608.47   316.3 1589.12   355.9 1564.84   365.7 1559.76
   390.4 1551.16   425.2 1547.37   479.8 1539.53   484.6 1539.51   494.8 1539.81
   524.3 1541.74   544.1 1550.95   578.8  1571.2   583.8 1573.06   618.4 1580.39
     648 1600.09   657.9 1605.74   712.3 1630.19     742    1649     831 1709.28
   850.7 1719.13   875.4 1735.96   900.2 1748.88   919.9 1763.42   929.8 1769.52
#Mann= 3 , 0 , 0
       0      .1       0   479.8    .045       0   494.8      .1       0
Bank Sta=479.8,494.8
XS Rating Curve= 0 ,0
Exp/Cntr=0.3,0.1

Type RM Length L Ch R = 1 ,4314.8  ,569.7,563.5,547.8
XS GIS Cut Line= 3
      1828282.58       194490.94     1828609.646      194729.779
     1828974.707      195081.755
#Sta/Elev= 30
       0  1761.1      30 1746.16      95  1708.8     135 1681.67     195  1642.8
     285 1595.37     335 1555.48     340 1552.71     345 1550.87     375 1541.57
     400 1529.87     405 1527.77   409.7 1526.83   419.9 1526.62   424.7  1526.7
   509.4 1531.46   549.2 1544.27   608.8    1568   618.8 1570.26   633.7 1572.31
   658.5 1572.64   663.5 1574.08   698.3 1588.67     758 1602.92   767.9 1606.14
   787.8 1610.76   807.7 1617.04   837.5 1625.11   867.4 1635.68   912.1  1657.1
#Mann= 3 , 0 , 0
       0      .1       0   409.7    .045       0   424.7      .1       0
Bank Sta=409.7,424.7
XS Rating Curve= 0 ,0
Exp/Cntr=0.3,0.1

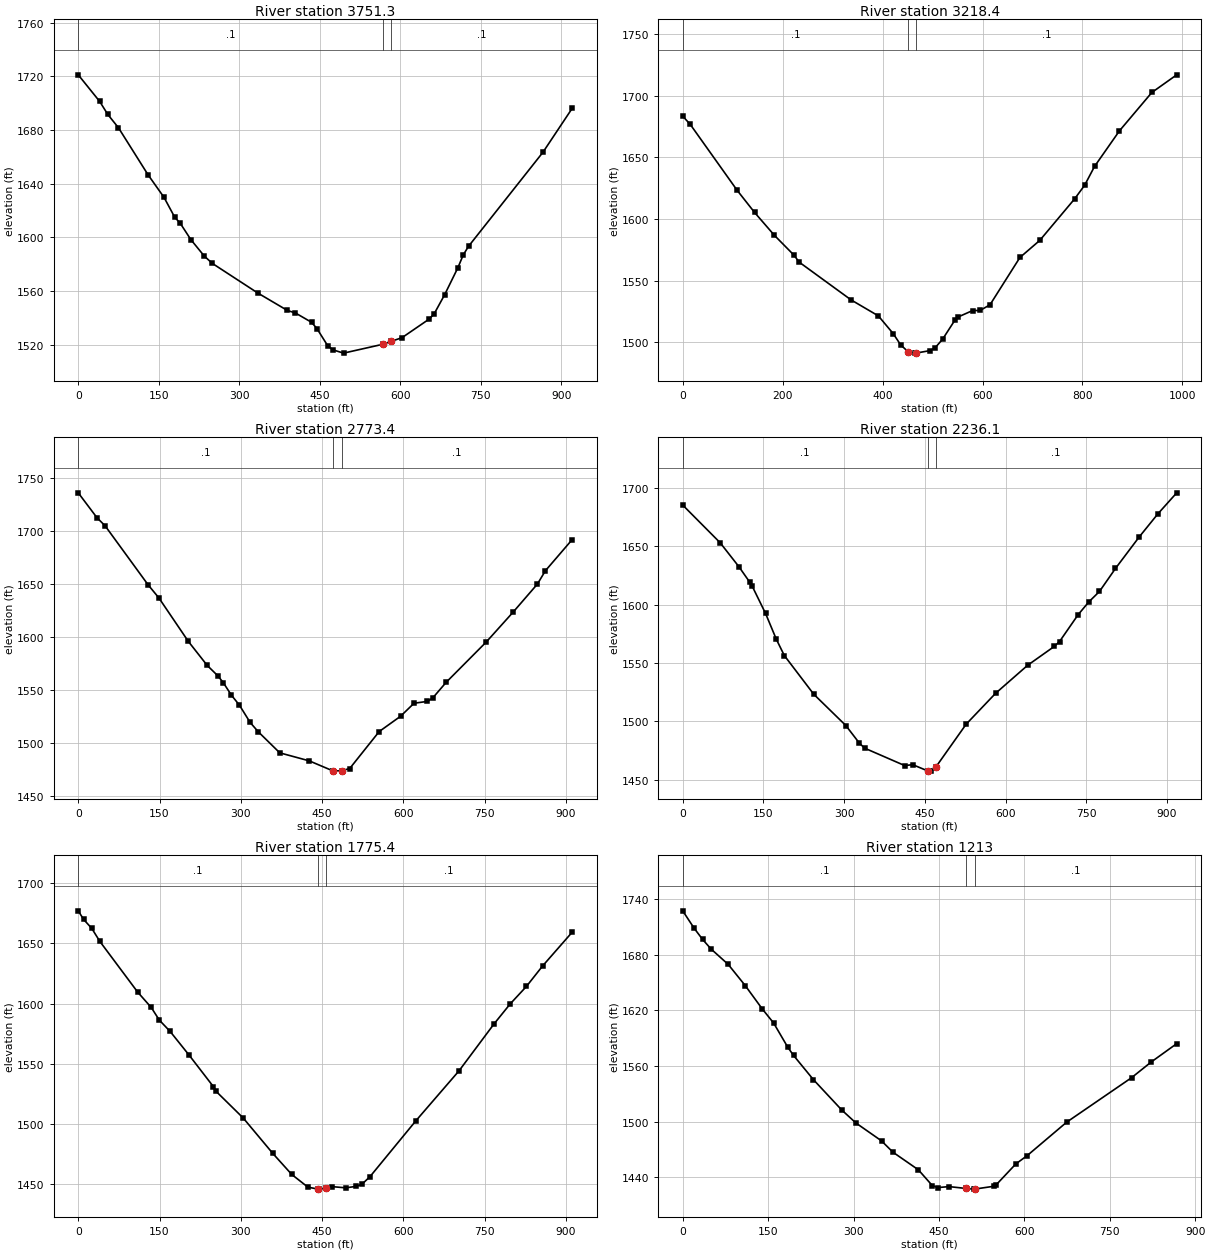
Type RM Length L Ch R = 1 ,3751.3  ,560.8,533,513.1
XS GIS Cut Line= 3
     1827893.108      195014.666     1828325.385      195170.715
     1828744.962      195360.956
#Sta/Elev= 30
       0 1721.02      40 1701.15      55 1691.52    74.9 1681.58   129.9 1646.61
   159.8  1629.7   179.8 1614.85   189.8 1610.53   209.8 1598.22   234.8 1585.96
   249.8  1580.5   334.7 1558.38   389.6 1545.44   404.6 1543.56   434.6 1536.63
   444.6 1531.97   464.5  1519.3   474.4 1516.09   494.3 1513.64   567.5 1520.24
   582.5 1522.34   603.2 1525.17   652.8 1538.75   662.7 1542.67   682.5  1557.1
   707.3 1577.32   717.2 1586.78   727.1 1593.25   865.8 1663.36   920.3 1696.12
#Mann= 3 , 0 , 0
       0      .1       0   567.5    .045       0   582.5      .1       0
Bank Sta=567.5,582.5
XS Rating Curve= 0 ,0
Exp/Cntr=0.3,0.1

Type RM Length L Ch R = 1 ,3218.4  ,438.6,444.9,451.3
XS GIS Cut Line= 3
     1827864.205      195943.461      1828219.19      195569.783
     1828690.591      195528.713
#Sta/Elev= 30
       0 1683.55    14.9 1676.97     109 1623.27   143.7 1605.38   183.4 1586.77
     223 1570.48   232.9 1565.01     337 1534.26   391.5 1521.29   421.2 1506.91
   436.1 1497.78   451.6 1491.93   465.8 1491.02   466.6 1491.03   495.6  1493.1
   505.5 1495.52   520.4 1502.51   545.3  1518.2   550.3 1520.24   580.2 1525.62
   595.1 1525.67     615 1530.32   674.8 1568.72   714.6 1582.62   784.4  1616.4
   804.3 1627.39   824.2 1642.73     874 1671.63   938.8 1702.79   988.6 1717.14
#Mann= 3 , 0 , 0
       0      .1       0   451.6    .045       0   466.6      .1       0
Bank Sta=451.6,466.6
XS Rating Curve= 0 ,0
Exp/Cntr=0.3,0.1

Type RM Length L Ch R = 1 ,2773.4  ,528.7,537.4,546
XS GIS Cut Line= 3
     1828027.528      196214.841     1828488.705      195942.958
     1828831.999      195789.486
#Sta/Elev= 30
       0 1736.07    34.7 1712.54    49.6 1704.98   128.9 1649.38   148.7 1637.11
   203.2 1596.02   237.9 1573.49   257.8 1563.54   267.7 1557.13   282.6 1545.44
   297.4 1535.98   317.2  1519.7   332.1 1510.96   371.8  1491.1   426.3 1483.53
   470.8 1473.89   470.9 1473.87   485.8 1474.38   500.7 1476.24   555.2 1511.15
   594.7 1525.58   619.5 1537.83   644.2 1539.57   654.1 1542.86   678.8 1557.55
   753.1 1595.72   802.5 1623.77   847.1 1650.11   861.9 1662.68   911.4 1692.08
#Mann= 3 , 0 , 0
       0      .1       0   470.8    .045       0   485.8      .1       0
Bank Sta=470.8,485.8
XS Rating Curve= 0 ,0
Exp/Cntr=0.3,0.1

Type RM Length L Ch R = 1 ,2236.1  ,458.7,460.7,462.7
XS GIS Cut Line= 3
     1828145.419      196549.063     1828745.027      196459.372
     1829032.681      196339.377
#Sta/Elev= 30
       0 1685.13    69.6 1652.87   104.4 1632.39   124.2 1619.36   129.2 1615.65
     154 1592.32   173.9 1570.33   188.8 1556.35   243.5 1523.22   303.1 1496.43
     328 1481.52   337.9 1477.08   412.5 1462.14   427.4 1462.91     455 1457.63
   457.2 1457.38   462.2 1457.48     470 1460.61   526.8  1497.6   581.4 1523.97
   640.9 1547.95   690.4 1564.09   700.3 1568.32   734.9 1591.35   754.7 1602.24
   774.5  1611.2   804.2 1630.86   848.7 1658.07   883.3 1677.76     918  1695.6
#Mann= 3 , 0 , 0
       0      .1       0     455    .045       0     470      .1       0
Bank Sta=455,470
XS Rating Curve= 0 ,0
Exp/Cntr=0.3,0.1

Type RM Length L Ch R = 1 ,1775.4  ,560.6,562.3,563.9
XS GIS Cut Line= 3
     1828127.961      196999.797      1828486.82      196938.091
     1829033.265        196904.6
#Sta/Elev= 30
       0 1677.11      10 1669.92    24.9 1662.56    39.9 1651.68   109.7 1609.56
   134.7 1596.81   149.6  1586.3   169.6 1576.87   204.5 1557.24   249.4 1531.01
   254.4 1527.09   304.3    1505   359.1 1475.48     394 1458.03   423.8 1447.48
   442.6 1445.87   443.8 1445.84   457.6 1446.77   468.6 1447.91   493.5 1446.92
   513.4 1448.16   523.4 1449.87   538.3 1456.17   622.9 1502.56   702.6 1544.11
   767.3 1583.15   797.1 1599.76     827 1614.26   856.8 1631.24   911.6 1659.42
#Mann= 3 , 0 , 0
       0      .1       0   442.6    .045       0   457.6      .1       0
Bank Sta=442.6,457.6
XS Rating Curve= 0 ,0
Exp/Cntr=0.3,0.1

Type RM Length L Ch R = 1 ,1213    ,417.8,432,445.1
XS GIS Cut Line= 4
     1828155.768      197399.866     1828550.901      197484.661
     1828731.834      197482.776     1829010.773      197528.009
#Sta/Elev= 30
       0 1727.63      20  1708.9    34.9 1696.78    49.9 1686.34    79.8 1669.84
   109.8 1646.92   139.7 1621.71   159.7 1606.46   184.6 1580.27   194.6 1571.53
   229.5 1545.36   279.4 1512.49   304.3 1498.49   349.2  1479.2   369.2    1467
   413.9 1447.96   438.4 1430.91   448.1 1428.77   467.7 1429.82   498.2  1427.8
   511.7  1427.1   513.2 1427.19     546 1430.15   550.8 1431.92   585.1 1454.34
   604.9 1463.25   674.3 1499.39   788.3 1547.42     823 1564.47   867.6  1584.2
#Mann= 3 , 0 , 0
       0      .1       0   498.2    .045       0   513.2      .1       0
Bank Sta=498.2,513.2
XS Rating Curve= 0 ,0
Exp/Cntr=0.3,0.1

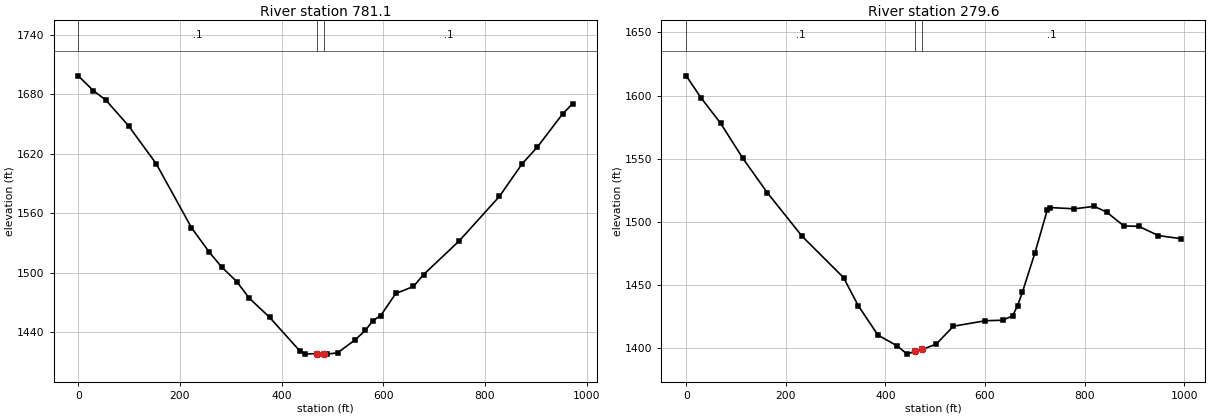
Type RM Length L Ch R = 1 ,781.1   ,508.2,501.4,495.7
XS GIS Cut Line= 4
     1828107.676      197520.701     1828447.241      197831.449
     1828567.863      197910.608     1828872.834      198116.617
#Sta/Elev= 30
       0 1698.82    29.7 1683.86    54.4  1674.3      99 1648.31   153.4 1610.11
   222.7 1545.69   257.4 1521.15   282.1 1506.01   311.8 1491.25   336.6 1474.42
   376.2 1455.37   435.6  1421.5   445.4 1418.36   468.7 1418.61   483.7 1418.29
   490.1 1418.16     510 1419.51   544.9 1432.64   564.8 1442.21   579.7 1452.06
   594.6 1456.85   624.5 1479.31   659.3 1486.38   679.2 1498.39   748.8  1532.1
   828.4 1577.22   873.1 1610.12     903 1626.98   952.7 1660.42   972.6 1670.86
#Mann= 3 , 0 , 0
       0      .1       0   468.7    .045       0   483.7      .1       0
Bank Sta=468.7,483.7
XS Rating Curve= 0 ,0
Exp/Cntr=0.3,0.1

Type RM Length L Ch R = 1 ,279.6   ,275.8,279.6,283.4
XS GIS Cut Line= 4
     1827712.142      197942.422     1828034.487      198114.158
     1828209.766      198189.547     1828584.315      198414.463
#Sta/Elev= 30
       0 1615.65    29.6  1598.3    69.1 1578.03   113.5 1550.45   162.9 1523.04
     232 1488.86   315.9 1455.82   345.5 1433.54   384.8 1410.35     424 1401.62
   443.5  1395.2   459.1 1397.36   474.1 1398.88   502.2 1403.21   536.5  1417.3
   600.7 1421.65   635.5 1422.08   655.3  1425.5   665.3 1433.52   675.2 1444.44
     700 1475.12   724.8 1509.08   729.8 1511.33   779.4  1510.3   819.2 1512.25
     844 1507.78   878.8 1496.72   908.5 1496.46   948.2  1489.1   992.9 1486.69
#Mann= 3 , 0 , 0
       0      .1       0   459.1    .045       0   474.1      .1       0
Bank Sta=459.1,474.1
XS Rating Curve= 0 ,0
Exp/Cntr=0.3,0.1

Chan Stop Cuts=-1
Use User Specified Reach Order=0